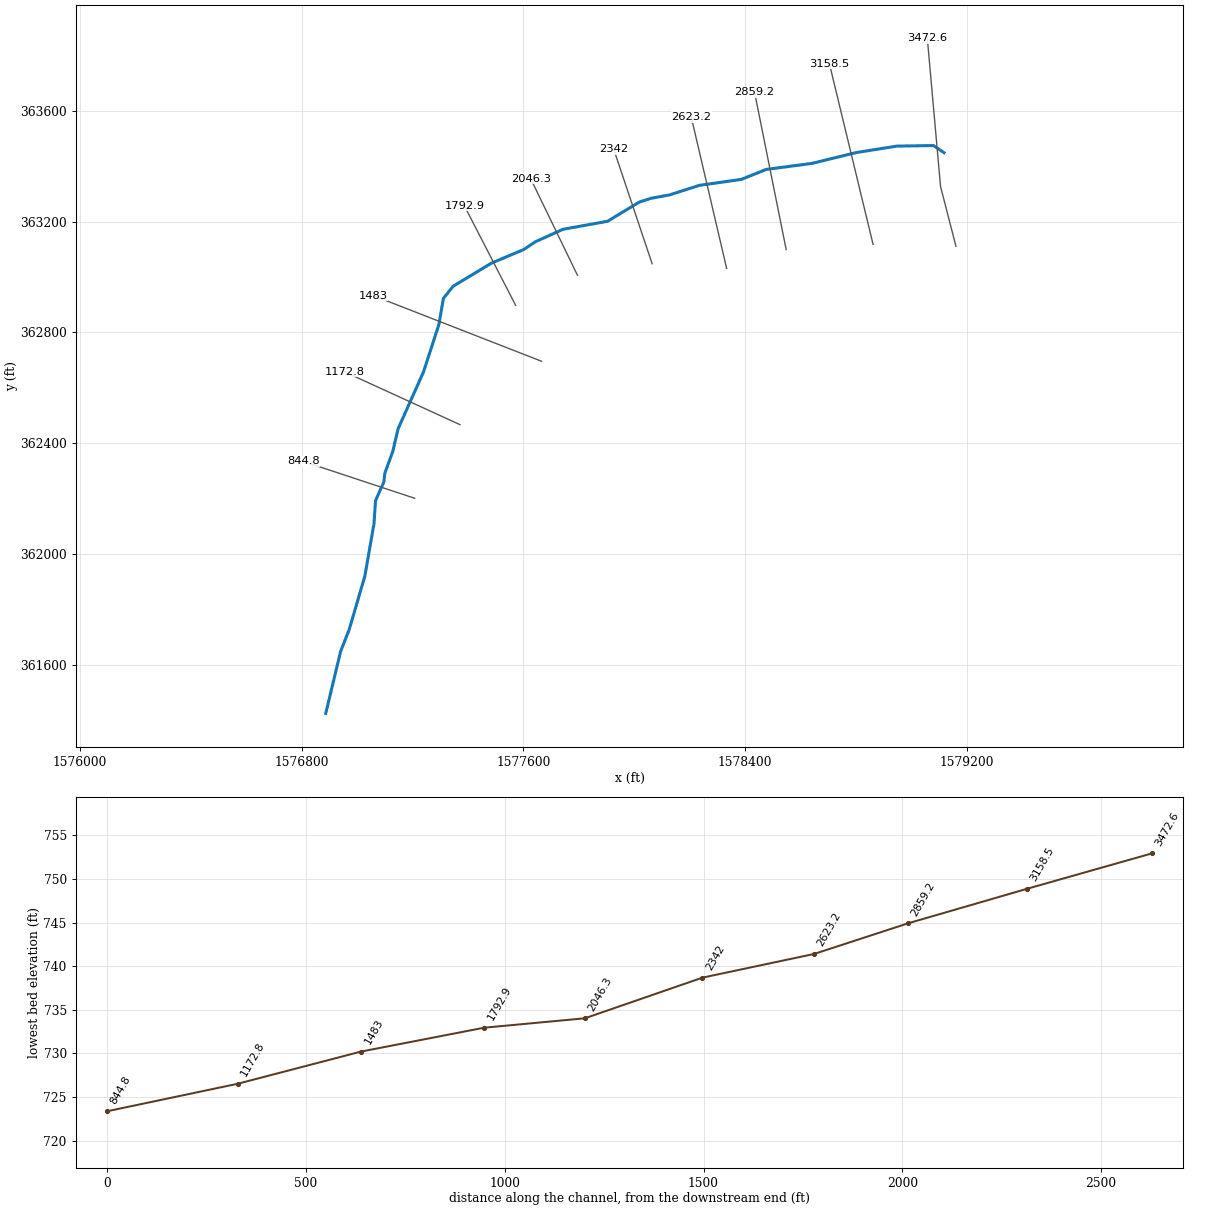
--- SWETWERBR.prj (project) ---

Proj Title=SWETWERBR
Current Plan=p01
Default Exp/Contr=0,0
English Units
Geom File=g01
Flow File=f01
Plan File=p01
BEGIN DESCRIPTION:
END DESCRIPTION:
DSS Export Rating Curves= 0
DSS Export Rating Curve Sorted= 0
DSS Export Volume Flow Curves= 0
DXF OffsetX= 0
DXF OffsetY= 0
DXF ScaleX= 0
DXF ScaleY= 0

--- SWETWERBR.p01 (plan) ---

Plan Title=Floodplain
Program Version=4.00
Geom File=g01
Flow File=f01
K Sum by GR=0
Std Step Tol=0.01
Critical Tol=0.01
Num of Std Step Trials=20
Max Error Tol=0.3
Flow Tol Ratio=0.001
Split Flow NTrial=30
Split Flow Tol=0.02
Split Flow Ratio=0.02
Log Output Level=0
Friction Slope Method=1
Unsteady Friction Slope Method=2
Unsteady Bridges Friction Slope Method=1
Global Log Level=0
CheckData=False
Run HTab=0
Run UNet=0
Run PostProcess=0
UNET Theta=0
UNET Theta Warmup=0
UNET ZTol=0
UNET ZSATol=0
UNET MxIter=0
UNET MaxInSteps=0
UNET DtIC=0
UNET DtMin=0
UNET MaxCRTS=0
UNET WFStab=0
UNET SFStab=0
UNET WFX=0
UNET SFX=0
UNET DSS MLevel=0
UNET DZMax Abort=0
UNET Convert EG Bridges=0
UNET Use Existing IB Tables=0
UNET Froude Limit=0
UNET Froude Power=0
Write IC File=0
Echo Input=False
Echo Output=False
Write Detailed=0

--- SWETWERBR.f01 (steady flow) ---

Flow Title=NFF Regression Equation
Program Version=4.00
Number of Profiles=1
Profile Names=P100yr
River Rch & RM=SWETWERBR,Main      ,3472.6
447.2147
River Rch & RM=SWETWERBR,Main      ,1792.9
476.5351
River Rch & RM=SWETWERBR,Main      ,1483
561.1856
Boundary for River Rch & Prof#=SWETWERBR,Main      ,1
Up Type=0
Dn Type=3
Dn Slope=0.010121

--- SWETWERBR.g01 (geometry) ---

Geom Title=Geometry
Program Version=4.00

River Reach=SWETWERBR       ,Main
Reach XY= 30
     1579118.604      363448.998      1579080.81       363474.69
     1578948.054      363472.685     1578801.353      363449.248
     1578641.631      363410.185     1578476.856      363388.534
     1578387.788      363352.747     1578236.249      363331.192
     1578127.742       363296.47     1578060.902      363284.317
     1578018.367      363270.428     1577904.166      363201.341
     1577743.193      363172.338     1577643.367      363127.199
       1577601.7      363099.421     1577484.513      363049.942
     1577346.492      362966.609      1577311.77      362923.206
     1577295.356      362828.736     1577239.947       362657.83
     1577147.979      362451.879      1577128.72      362369.818
     1577100.314      362292.181     1577096.831      362260.398
     1577066.598      362192.819     1577061.173      362110.082
     1577028.131      361920.616     1576971.331       361726.55
     1576940.565       361648.45     1576886.977      361425.021

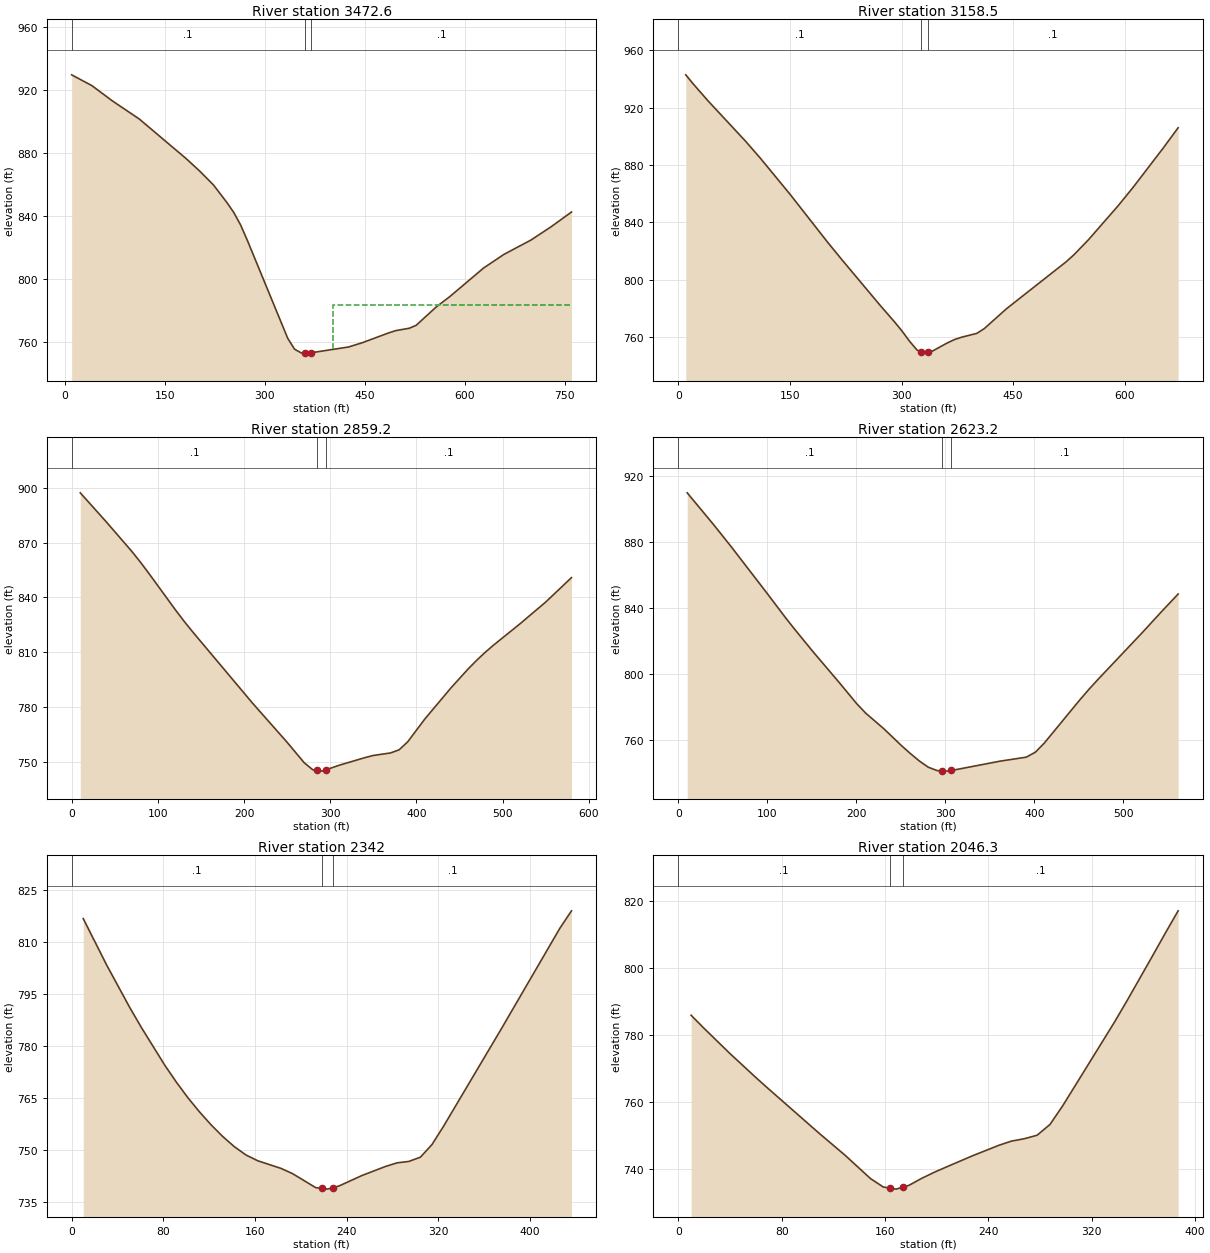
Type RM Length L Ch R = 1 ,3472.6  ,317.5,314.1,315.7
XS GIS Cut Line= 3
     1579161.832      363110.986     1579106.244        363326.8
      1579058.47      363861.726
#Sta/Elev= 30
    10.1  929.79    40.5  922.92    70.9   913.3   111.4  901.76   182.3  876.39
   202.6  868.45   222.9  859.79   243.1  848.59   253.3  842.31   263.4  834.51
   273.5  824.77   334.3   762.3   344.5  755.45   354.6  753.05   359.7     753
   364.7  752.94   369.7  753.19   425.5  756.85   445.8  759.51   486.3  765.89
   496.5  767.26   516.7  768.76   526.9  770.62   557.3  782.39   577.5   788.9
   628.2  807.07   658.6  815.69   699.1  824.79   729.5  833.29   759.9   842.6
#Mann= 3 , 0 , 0
    10.1      .1       0   359.7    .045       0   369.7      .1       0
#XS Ineff= 2 , 0
                          402.68          783.21
Permanent Ineff=
       F       F
Bank Sta=359.7,369.7
XS Rating Curve= 0 ,0
Exp/Cntr=0.3,0.1

Type RM Length L Ch R = 1 ,3158.5  ,300.1,299.4,298.6
XS GIS Cut Line= 2
     1578862.671      363117.849     1578704.907      363770.666
#Sta/Elev= 30
      10  942.96      20  936.64    40.1  924.71    90.2  896.75   110.3  884.78
   150.4  859.47   200.5  826.29   220.5  813.59   270.6  782.56   290.7  770.55
   300.7  764.22   310.7  757.17   320.8  750.99   325.8  749.93   330.8  748.88
   335.8   749.5   340.8  750.12   360.9  755.85   370.9  758.31   380.9  760.02
     401  762.63     411  765.94   441.1   779.9   521.2  812.62   531.3  817.33
   551.3  828.07   591.4  851.92   611.5  864.78   651.6  891.95   671.6  906.05
#Mann= 3 , 0 , 0
       0      .1       0   325.8    .045       0   335.8      .1       0
Bank Sta=325.8,335.8
XS Rating Curve= 0 ,0
Exp/Cntr=0.3,0.1

Type RM Length L Ch R = 1 ,2859.2  ,235.3,236,236.7
XS GIS Cut Line= 2
     1578549.006      363099.091     1578434.763      363667.585
#Sta/Elev= 30
      10  897.25      40  881.45      70  865.09      80  859.18      90  852.89
     120  833.44     130  827.23     140  821.37   209.9  782.11   249.9  760.76
   269.9  749.46   279.9  745.62   284.9  745.27   289.9  744.92   294.9  745.61
   309.9  748.07   339.9  752.26   349.9  753.49   369.9  754.86   379.9  756.58
   389.9  760.98   409.9  773.54   439.9  790.39   459.9  800.79   469.9  805.58
   479.9  810.01   489.9  814.05   519.9  825.46   549.9  837.43   579.9  850.84
#Mann= 3 , 0 , 0
       0      .1       0   284.9    .045       0   294.9      .1       0
Bank Sta=284.9,294.9
XS Rating Curve= 0 ,0
Exp/Cntr=0.3,0.1

Type RM Length L Ch R = 1 ,2623.2  ,279.2,281.1,282.9
XS GIS Cut Line= 2
     1578334.121      363031.089     1578206.277      363577.823
#Sta/Elev= 30
      10  909.92    40.1  890.35    60.2  876.76   100.3  848.66   120.3  834.41
   130.3  827.59   150.4  814.32   180.5  795.22   200.5  782.19   210.6  776.48
   230.6   767.2   250.7  756.85   260.7  752.06   270.7  747.57   280.7  743.82
   290.8  741.73   295.8  741.57   300.8  741.41   305.8  741.81   310.8   742.2
     361   747.4     391  749.88   401.1  752.87   411.1  758.38   451.2  784.66
   461.2   790.9   471.2  796.79   521.4   825.4   541.4  837.15   561.5  848.66
#Mann= 3 , 0 , 0
       0      .1       0   295.8    .045       0   305.8      .1       0
Bank Sta=295.8,305.8
XS Rating Curve= 0 ,0
Exp/Cntr=0.3,0.1

Type RM Length L Ch R = 1 ,2342    ,293.2,295.7,298.4
XS GIS Cut Line= 2
     1578065.159      363048.078     1577926.436      363461.529
#Sta/Elev= 30
    10.1  816.66    30.4  803.36    50.7  791.02    60.9  785.24    81.1  774.48
    91.3  769.55   101.4  765.04   111.6  760.93   121.7   757.2   131.8  753.86
     142   750.9   152.1  748.53   162.3  746.87   182.6  744.67   192.7  743.16
     213  739.11   218.1   738.9   223.1  738.69   228.1  739.14   233.3   739.6
   253.5  742.64   273.8  745.22     284  746.27   294.1  746.66   304.3   747.9
   314.4  751.54   324.5  756.82   375.3  785.11     426  813.89   436.1  818.89
#Mann= 3 , 0 , 0
       0      .1       0   218.1    .045       0   228.1      .1       0
Bank Sta=218.1,228.1
XS Rating Curve= 0 ,0
Exp/Cntr=0.3,0.1

Type RM Length L Ch R = 1 ,2046.3  ,252.9,253.4,253.9
XS GIS Cut Line= 2
     1577795.547      363006.608     1577626.903      363354.777
#Sta/Elev= 28
     9.9  785.83    19.8  781.98    39.7  774.52    59.5  767.46    69.4  764.05
   109.1  750.64     129  744.15   148.8  737.16   158.7  734.65   163.6  734.34
   168.6  734.03   173.6   734.6   178.6  735.17   188.5  737.26   198.4   739.1
   208.3  740.76   228.1  744.02     248  747.07   257.9  748.34   267.8  749.04
   277.7  750.08   287.7   753.3   297.6  758.89   337.3  783.59   347.2  790.07
     367  803.47   376.9  810.25   386.9  816.94
#Mann= 3 , 0 , 0
       0      .1       0   163.6    .045       0   173.6      .1       0
Bank Sta=163.6,173.6
XS Rating Curve= 0 ,0
Exp/Cntr=0.3,0.1

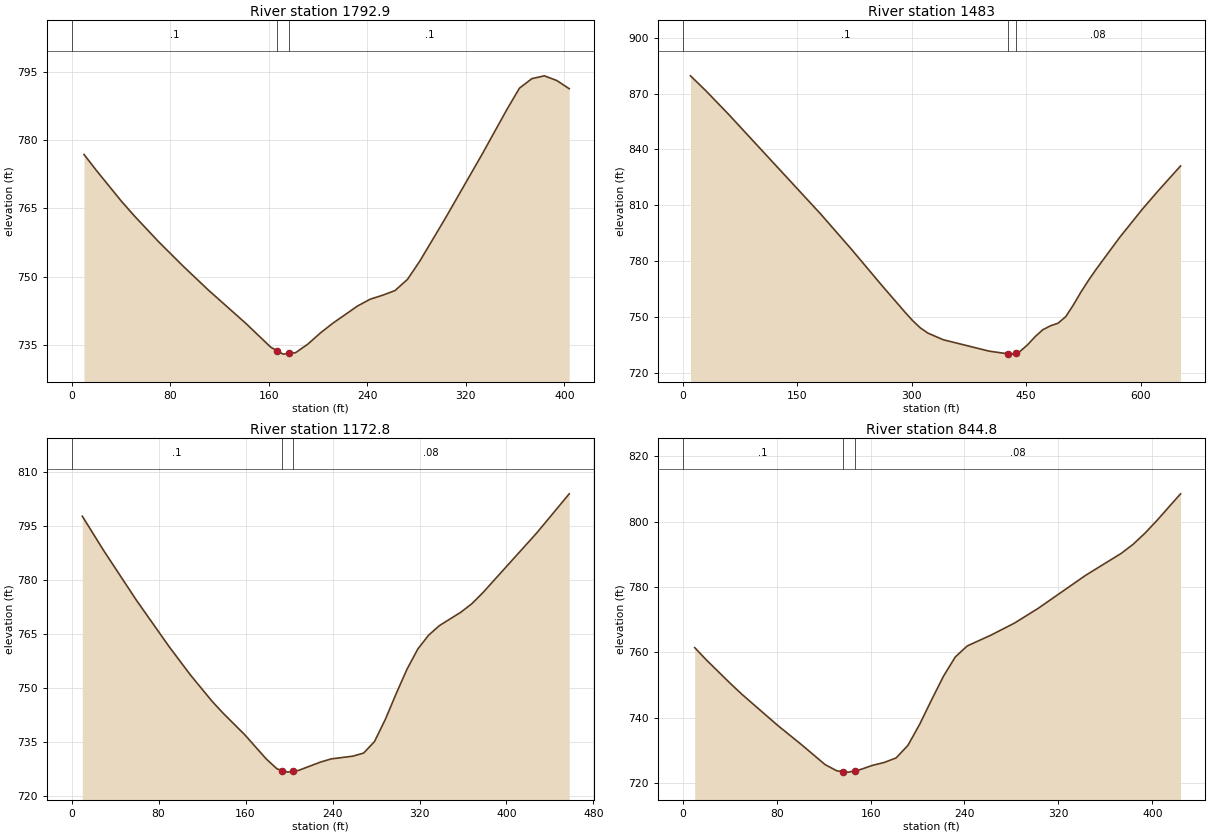
Type RM Length L Ch R = 1 ,1792.9  ,295.5,309.9,324.3
XS GIS Cut Line= 2
     1577572.501      362897.806     1577387.537      363256.855
#Sta/Elev= 30
    10.1  776.82    20.2   773.3    40.4  766.57    50.5  763.46    70.7  757.63
    90.9   752.2   111.1  747.01   141.4  739.72   161.6  734.49   166.7  733.71
   171.7  732.95   176.7  733.11   181.8  733.26   191.8  735.15   201.9  737.59
     212  739.73   232.2  743.54   242.3  745.01   252.4  745.89   262.5  746.91
   272.6  749.36   282.7  753.42   302.9  762.59   333.2  776.87   353.4  786.74
   363.5  791.39   373.6  793.48   383.7   794.1   393.8  793.07   403.9  791.27
#Mann= 3 , 0 , 0
       0      .1       0   166.7    .045       0   176.7      .1       0
Bank Sta=166.7,176.7
XS Rating Curve= 0 ,0
Exp/Cntr=0.3,0.1

Type RM Length L Ch R = 1 ,1483    ,311.1,310.2,309.3
XS GIS Cut Line= 2
     1577666.099       362696.02     1577058.408      362933.166
#Sta/Elev= 30
      10  879.52    30.1  871.54    60.2  858.76   180.6   805.4   220.8  786.56
   260.9  767.04     291  752.79   301.1  748.23   311.1  744.35   321.1  741.51
   341.2  737.94   401.4  731.81   426.5  730.35   431.5  730.21   436.5  730.88
   441.6  731.56   451.6  735.12   461.6  739.52   471.7  743.28   481.7  745.38
   491.8   746.8   501.8  750.29   511.8  756.55   521.9  763.59   531.9  769.94
   541.9  775.83     572  792.55   602.1  807.91   622.2  817.45   652.3  831.16
#Mann= 3 , 0 , 0
       0      .1       0   426.5    .045       0   436.5     .08       0
Bank Sta=426.5,436.5
XS Rating Curve= 0 ,0
Exp/Cntr=0.3,0.1

Type RM Length L Ch R = 1 ,1172.8  ,325.8,328,330.2
XS GIS Cut Line= 2
     1577371.533      362467.216     1576955.363      362657.621
#Sta/Elev= 30
     9.9  797.63    29.8  787.97    59.7  774.27    89.5  761.49   109.4  753.49
   129.3  746.19   139.3  742.93   159.2  736.94   179.1  730.17     189  727.42
     194  726.97     199  726.52     204  726.77   208.9  727.01   228.8   729.3
   238.8  730.19   258.7  730.96   268.6  731.81   278.6  735.01   288.5  741.12
   298.5  748.29   308.4  755.05   318.4   760.7   328.3  764.55   338.3  767.23
   358.2  770.99   368.1  773.31   378.1  776.32   427.8  792.97   457.7  803.85
#Mann= 3 , 0 , 0
       0      .1       0     194    .045       0     204     .08       0
Bank Sta=194,204
XS Rating Curve= 0 ,0
Exp/Cntr=0.3,0.1

Type RM Length L Ch R = 1 ,844.8   ,843.8,844.8,845.8
XS GIS Cut Line= 2
     1577208.012      362201.468     1576805.442      362334.751
#Sta/Elev= 30
    10.1  761.48    20.2  757.66    40.4  750.54    50.5  747.14    80.8  737.68
     101  731.81   121.2  725.68   131.3  723.75   136.4  723.56   141.4  723.37
   146.4  723.77   151.5  724.18   161.5  725.43   171.6  726.33   181.7  727.71
   191.8  731.56   201.9  738.09     212  745.52   222.1  752.73   232.2  758.64
   242.3  761.99   262.5  765.29   282.7  769.01   302.9  773.53   343.3  783.63
   373.6  790.34   383.7  793.11   393.8  796.51   403.9  800.36   424.1  808.56
#Mann= 3 , 0 , 0
       0      .1       0   136.4    .045       0   146.4     .08       0
Bank Sta=136.4,146.4
XS Rating Curve= 0 ,0
Exp/Cntr=0.3,0.1

Chan Stop Cuts=-1
Use User Specified Reach Order=0